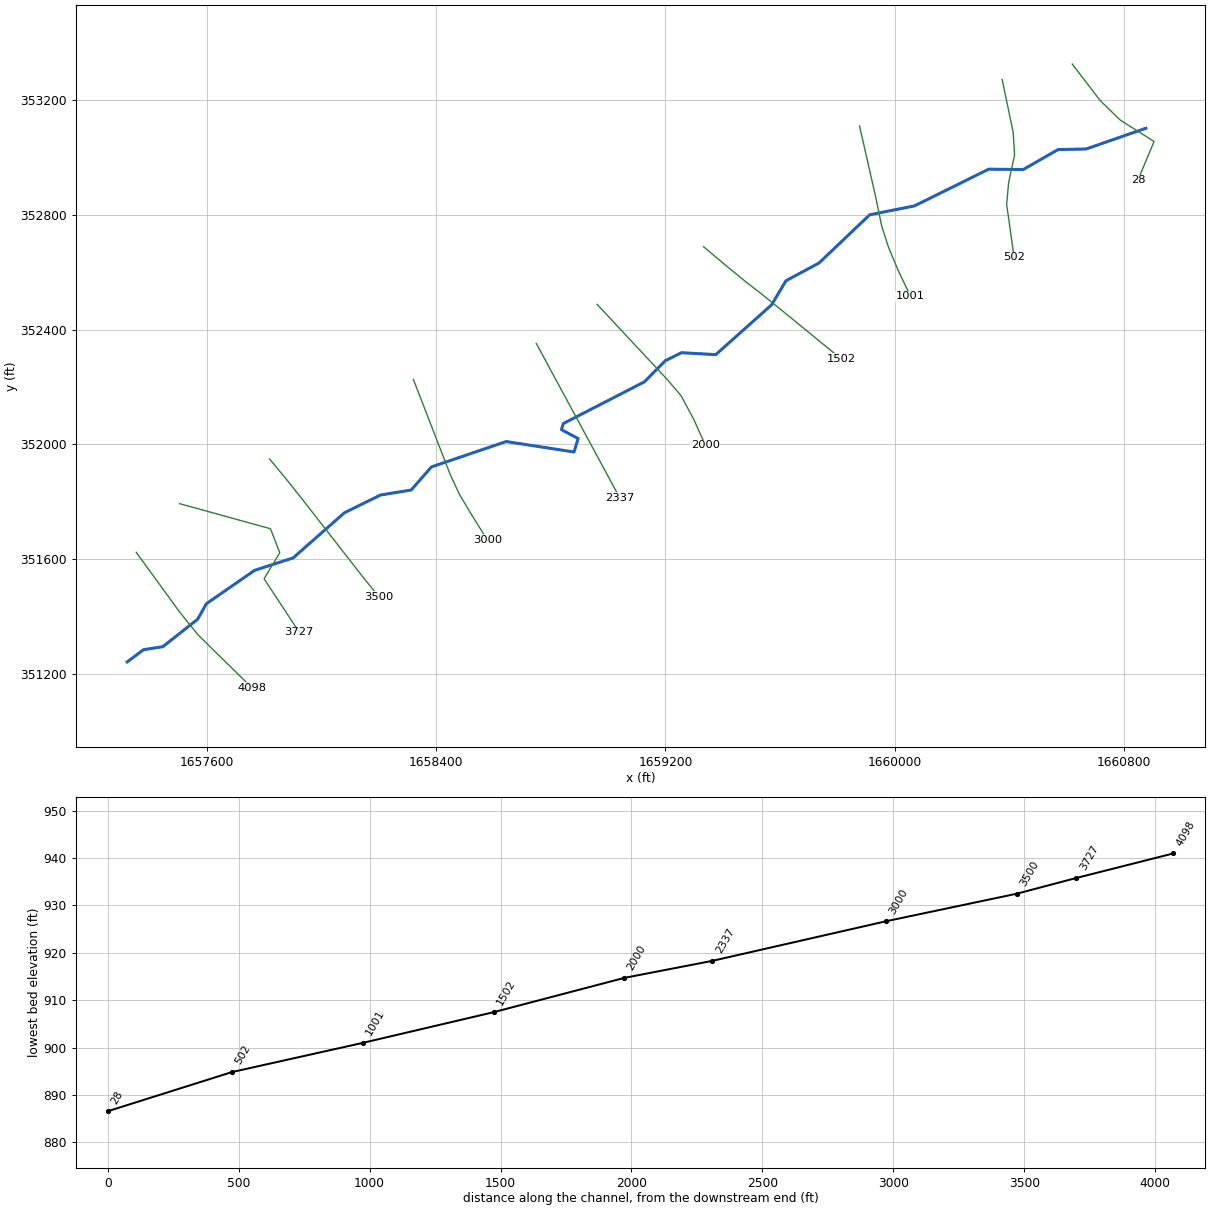
--- SLBCMPRN.prj (project) ---

Proj Title=SLBCMPRN
Current Plan=p01
Default Exp/Contr=0,0
English Units
Geom File=g01
Flow File=f01
Plan File=p01
BEGIN DESCRIPTION:
---------- MODELED AS PART OF WVEMD CTP PROGRAM, 2023----------
Stream Name: Slabcamp Run
Flood Zone:  AFH
Wetzel County, WV
HEC-RAS Version: RAS 6.3
Vertical Datum: NAVD88
Projection: NAD 1983 StatePlane West Virginia S FIPS 4702 (US Feet)
Terrain: 1-meter West Virginia FEMA R3 South Central (collected 2018-2020)
Land Use: 2019 NLCD
Hydrologic Method:
WV 2010 Regional Regression Equations
Additional Model Notes:
None
END DESCRIPTION:
DSS Export Rating Curves= 0
DSS Export Rating Curve Sorted= 0
DSS Export Volume Flow Curves= 0
DXF OffsetX= 0
DXF OffsetY= 0
DXF ScaleX= 0
DXF ScaleY= 0

--- SLBCMPRN.p01 (plan) ---

Plan Title=Floodplain
Program Version=6.30
Short Identifier=Floodplain
Geom File=g01
Flow File=f01
Subcritical Flow
K Sum by GR= 0
Std Step Tol= 0.01
Critical Tol= 0.01
Num of Std Step Trials= 20
Max Error Tol= 0.3
Flow Tol Ratio= 0.001
Split Flow NTrial= 30
Split Flow Tol= 0.02
Split Flow Ratio= 0.02
Log Output Level= 0
Friction Slope Method= 1
Unsteady Friction Slope Method= 2
Unsteady Bridges Friction Slope Method= 1
Parabolic Critical Depth
Global Vel Dist= 0 , 0 , 0
Global Log Level= 0
CheckData=False
Encroach Param=-1 ,0,0, 0
Mapping Interval=1HOUR
Computation Time Step Use Courant=        0
Computation Time Step Use Time Series=    0
Computation Time Step Count To Double=0
Computation Time Step Max Doubling=0
Computation Time Step Max Halving=0
Computation Time Step Residence Courant=0
Run HTab= 0
Run UNet= 0
Run Sediment= 0
Run PostProcess= 0
Run WQNet= 0
Run RASMapper=-1
UNET Theta= 0
UNET Theta Warmup= 0
UNET ZTol= 0
UNET ZSATol= 0
UNET MxIter= 0
UNET Max Iter WO Improvement= 0
UNET MaxInSteps= 0
UNET DtIC= 0
UNET DtMin= 0
UNET MaxCRTS= 0
UNET WFStab= 0
UNET SFStab= 0
UNET WFX= 1
UNET SFX= 1
UNET Gravity=32.17405
UNET 1D Methodology=Finite Difference
UNET DSS MLevel= 1
UNET Pardiso=0
UNET DZMax Abort= 0
UNET Use Existing IB Tables= 0
UNET Froude Reduction=False
UNET Froude Limit= 0
UNET Froude Power= 0
UNET D1 Cores= 0
UNET WindReference=Eulerian
UNET WindDragFormulation=Hsu (1988)
UNET D2 Coriolis=0
UNET D2 Cores= 0
UNET D2 Theta= 1
UNET D2 Theta Warmup= 1
UNET D2 Z Tol= 0.01
UNET D2 Volume Tol= 0.01
UNET D2 Max Iterations= 20
UNET D2 Equation= 0
UNET D2 RampUpFraction=0.1
UNET D2 TimeSlices= 1
UNET D2 Turbulence Formulation=Non-Conservative (original)
UNET D2 Eddy Viscosity=0.3
UNET D2 Transverse Eddy Viscosity=0.1
UNET D2 Smagorinsky Mixing=0
UNET D2 BCVolumeCheck=0
UNET D2 Cores=0
UNET D2 SolverType=PARDISO (Direct)
UNET D2 Minimum Iterations= 3
UNET D2 Maximum Iterations= 30
UNET D2 Restart Number= 10
UNET D2 Relaxation Coeff=1.3
UNET D2 SOR Precondition Iterations= 10
UNET D2 ILUT Maximum Fill= 8
UNET D2 ILUT Tolerance=1E-08
UNET D2 Convergence Tolerance=0.00001
UNET D1D2 MaxIter= 0
UNET D1D2 ZTol=0.01
UNET D1D2 QTol=0.1
UNET D1D2 MinQTol=1
Write IC File= 0
Write IC File at Fixed DateTime=0
Write IC File at Sim End=0
Echo Input=False
Echo Parameters=False
Echo Output=False
Write Detailed= 0
HDF Write Warmup=0
HDF Write Time Slices=0
HDF Flush=0
HDF Compression= 1
HDF Chunk Size= 1
HDF Spatial Parts= 1
HDF Use Max Rows=0
HDF Fixed Rows= 1
Calibration Method= 0
Calibration Iterations= 20
Calibration Max Change=0.05
Calibration Tolerance=0.2
Calibration Maximum=1.5
Calibration Minimum=0.5
Calibration Optimization Method= 1
WQ AD Non Conservative
WQ ULTIMATE=-1
WQ Max Comp Step=1HOUR
WQ Output Interval=15MIN
WQ Output Selected Increments= 0
WQ Output face flow=0
WQ Output face velocity=0
WQ Output face area=0
WQ Output face dispersion=0
WQ Output cell volume=0
WQ Output cell surface area=0
WQ Output cell continuity=0
WQ Output cumulative cell continuity=0
WQ Output face conc=0
WQ Output face dconc_dx=0
WQ Output face courant=0
WQ Output face peclet=0
WQ Output face adv mass=0
WQ Output face disp mass=0
WQ Output cell mass=0
WQ Output cell source sink temp=0
WQ Output nsm pathways=0
WQ Output nsm derived pathways=0
WQ Create Restart=0
WQ Fixed Restart=0
WQ System Summary=0
WQ Write To DSS=0
Sorting and Armoring Iterations= 10
XS Update Threshold= 0.02
Bed Roughness Predictor= 0
Hydraulics Update Threshold= 0.02
Energy Slope Method= 1
Volume Change Method= 1
Sediment Retention Method= 0
Sediment TS Multiplier= 1
Warm Up Method= 0
XS Weighting Method= 0
Number of US Weighted Cross Sections= 1
Number of DS Weighted Cross Sections= 1
Upstream XS Weight=0
Main XS Weight=1
Downstream XS Weight=0
Number of DS XS's Weighted with US Boundary= 1
Upstream Boundary Weight= 1
Weight of XSs Associated with US Boundary= 0
Number of US XS's Weighted with DS Boundary= 1
Downstream Boundary Weight= 0.5
Weight of XSs Associated with DS Boundary= 0.5
Percentile Method= 0
Sediment Output Level= 3
Mass or Volume Output= 0
Output Increment Type= 1
Profile and TS Output Increment= 1
Transport Output Increment 1
XS Output Flag= 0
XS Output Increment= 10
Read HDF5 Sediment Hotstart= 0
Sediment Hotstart Type= 0
Write Gradation File= 0
Read Gradation Hotstart= 0
Write HDF5 File= 1
Write Binary Output= 1
Write DSS Sediment File= 0
DSS Sediment Output Type= 1
SV Curve= 0
Specific Gage Flag= 0
Subcell Erosion Methods= 0
Subcell Deposition Methods= 0
Advection Scheme= 1
Matrix Solver= 0
Implicit Weighting Factor= 1
Maximum Outer Loop Convergence Iterations= 5
Convergence Maximum Absolute= 0.001
Convergence RMSE= 0.0001
Grain Fractions Max Abs Error= 0.001
Max Subgrid Regions= 1
Max Subgrid Length Scale= 3.402823E+38
Initial Layer Thickness= 3.402823E+38
Min Layer Thickness= 3.402823E+38
Max Layer Thickness= 3.402823E+38
Number of Layers= 5

--- SLBCMPRN.f01 (steady flow) ---

Flow Title=Flow
Program Version=6.31
Number of Profiles= 1
Profile Names=F01pct
River Rch & RM=SLBCMPRN,Main,4098
     683
Boundary for River Rch & Prof#=SLBCMPRN,Main            , 1
Up Type= 0
Dn Type= 3
Dn Slope=0.01726
DSS Import GetInterval= 0
DSS Import GetPeak= 0
DSS Import FillOption= 0

--- SLBCMPRN.g01 (geometry) ---

Geom Title=Geometry
Program Version=6.30

River Reach=SLBCMPRN        ,Main
Reach XY= 30
     1657322.908      351241.751     1657380.005      351284.432
     1657447.277       351294.89     1657569.102      351390.994
     1657599.064      351444.698      1657767.81      351561.436
     1657901.507      351604.399     1658080.428      351761.839
     1658206.211      351823.741     1658313.338      351841.266
     1658384.002      351921.823     1658644.611      352010.295
     1658881.195      351973.832     1658895.611      352020.753
     1658837.383      352051.563     1658843.884      352073.045
     1659126.258       352218.33     1659199.749      352292.386
     1659255.998      352320.086     1659375.279      352313.303
     1659570.029      352486.854      1659620.06      352570.803
     1659735.667      352632.988     1659912.044      352800.886
     1660068.354      352831.978     1660327.267      352960.021
     1660447.961      352958.891     1660568.939      353028.424
     1660666.738      353030.403     1660875.304      353102.768

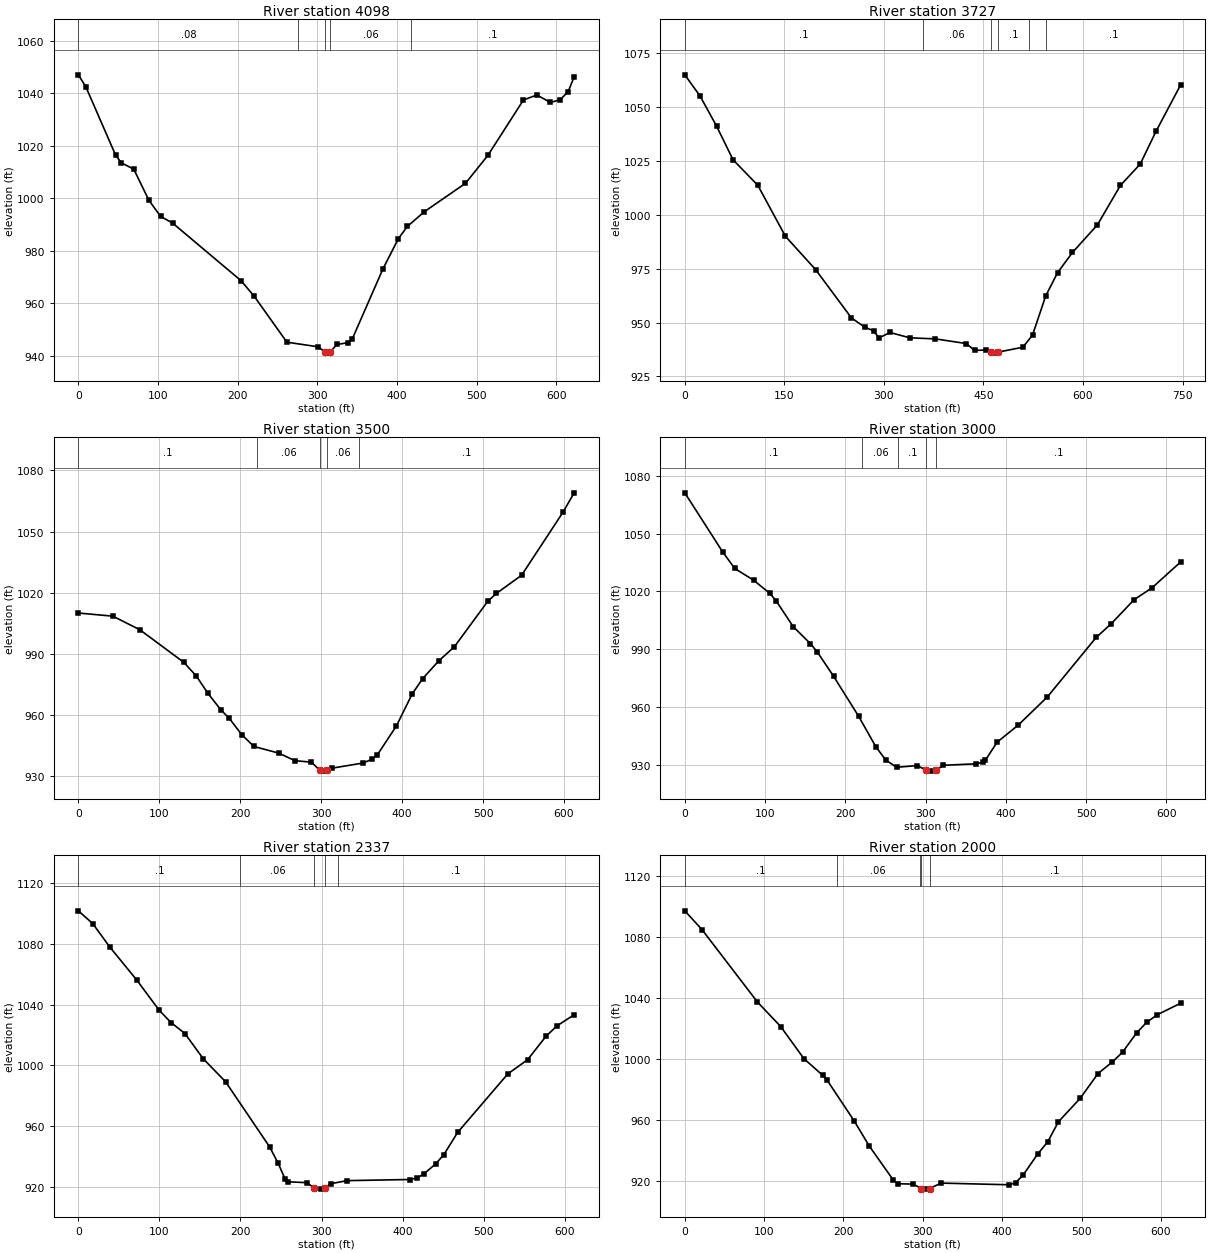
Type RM Length L Ch R = 1 ,4098    ,370.7,370.7,370.7
XS GIS Cut Line= 6
1657354.52344534351624.1408366981657505.12550635351416.883377192
1657569.02465676351337.5754649461657624.76535893351282.393816781
1657689.21601743351219.2679587731657757.46358435351152.180166436
#Sta/Elev= 30
       0 1046.96     9.4 1042.42    46.7 1016.43    53.9 1013.47    69.6 1011.03
    88.5  999.22   103.3  993.02   118.3  990.51   204.2  968.57   220.5  962.74
   261.8  945.14   301.2  943.37   309.8  941.29   312.6  940.97   315.7  941.29
   324.7  944.27   338.8  944.96     344  946.46   382.3  973.01   401.8   984.6
     413  989.22   434.5  994.86     486 1005.65     514 1016.24   558.8  1037.4
   575.6 1039.28   592.5 1036.45   604.8 1037.43   614.9  1040.6   622.4 1046.18
#Mann= 5, -1 ,  0
       0    0.08       0   276.2    0.06       0   309.8   0.045       0
   315.7    0.06       0  418.04     0.1       0
Bank Sta=309.8,315.7
XS Rating Curve= 0 ,0
Exp/Cntr(USF)=0,0
Exp/Cntr=0.3,0.1

Type RM Length L Ch R = 1 ,3727    ,226.9,226.9,226.9
XS GIS Cut Line= 5
1657506.08091595351793.6953188161657822.59605077351706.304829154
1657855.18696237351622.6053336661657800.43102079 351531.76024876
 1657922.7649604351345.652868935
#Sta/Elev= 30
       0 1064.97    22.9 1055.18    47.8  1041.2    72.7 1025.53     110 1013.69
   151.5  990.06   197.1  974.54   251.1  952.12   271.8  947.71   284.3  946.19
   292.6  942.85   309.2  945.37   338.8   942.9   377.5   942.4   424.1  940.24
   436.5  937.05   453.3  937.23  460.85  936.26   467.3  935.79     472  936.26
   509.3  938.53   523.9  944.17   543.7  962.32   561.6  973.15   584.1  982.53
   621.7  995.36   656.3 1013.64   686.1 1023.53     710 1038.79     747  1060.3
#Mann= 6, -1 ,  0
       0     0.1       0  358.36    0.06       0  460.85   0.045       0
     472     0.1       0  518.18    0.06       0  544.25     0.1       0
Bank Sta=460.85,472
XS Rating Curve= 0 ,0
Exp/Cntr(USF)=0,0
Exp/Cntr=0.3,0.1

Type RM Length L Ch R = 1 ,3500    ,500,500,500
XS GIS Cut Line= 6
1657819.69735184351949.3941685111657879.45805909351877.109208092
1657933.99994476351808.6818515061658041.56239368351670.640789002
1658141.44309942351542.4609272631658200.35144617351469.511926174
#Sta/Elev= 30
       0 1010.05    42.6 1008.52      76 1001.85   130.3  985.86   145.7  979.18
   160.1  970.64   176.4  962.41   186.5  958.39   201.8   950.4     217  944.57
   247.4  941.34   267.7   937.6     288  936.88   298.6932.7982   302.6  932.48
   307.4932.7952     314  933.97   351.1  936.41   362.5  938.21   369.1  940.27
     393  954.67   412.5  970.37   425.5   977.9   445.2  986.53   464.6  993.51
     506 1015.88   516.6 1019.69   547.7 1028.61   598.9 1059.57   612.6 1069.03
#Mann= 5, -1 ,  0
       0     0.1       0  221.29    0.06       0   298.6   0.045       0
   307.4    0.06       0  346.29     0.1       0
Bank Sta=298.6,307.4
XS Rating Curve= 0 ,0
Exp/Cntr(USF)=0,0
Exp/Cntr=0.3,0.1

Type RM Length L Ch R = 1 ,3000    ,663.2,663.2,663.2
XS GIS Cut Line= 6
1658321.12909175352226.5524068331658355.00303976 352139.13624309
1658449.85094717351894.3706565051658481.63205159351825.999402165
1658527.63950551351749.0999496731658578.96519026351667.314352095
#Sta/Elev= 30
       0 1071.22    47.1 1040.58    62.2 1031.95    85.8 1025.81   105.9    1019
   113.7 1015.18   135.1  1001.7   156.6  992.85   165.2  988.49   185.4  975.93
   216.7  955.08   238.1  939.27   250.4  932.46   263.8  928.65   289.6  929.55
   300.9927.1376   306.7  926.66     313  927.13   322.3   929.7   362.7  930.46
   371.5  931.23   374.4  932.24   389.1  941.68   415.6  950.62   451.9  965.27
   512.6  996.12   531.4 1003.24   559.7 1015.67   582.4 1021.96   617.8  1035.3
#Mann= 5, -1 ,  0
       0     0.1       0  221.25    0.06       0  266.25     0.1       0
   300.9   0.045       0     313     0.1       0
Bank Sta=300.9,313
XS Rating Curve= 0 ,0
Exp/Cntr(USF)=0,0
Exp/Cntr=0.3,0.1

Type RM Length L Ch R = 1 ,2337    ,336.8,336.8,336.8
XS GIS Cut Line= 2
1658749.69800505352352.1774466781659040.58366188351814.107264561
#Sta/Elev= 30
       0 1101.88    17.8 1093.46    38.7 1078.08    72.3 1056.09    99.6 1036.39
   114.4 1028.17   131.5 1020.95   154.2 1004.23   181.6  989.16     236  946.18
   246.5  935.37   255.3  924.69   258.8  923.15   281.5  922.58   291.1  919.15
   299.6  918.31   304.1919.1519   311.4  921.89   331.5  923.91   408.9  924.66
   417.7  925.58   426.5  928.48   440.7  934.87   450.9  941.03   467.9  955.68
   529.8  994.29   554.3 1003.69     577 1019.16   590.7 1026.07   611.7 1033.32
#Mann= 5, -1 ,  0
       0     0.1       0     200    0.06       0   291.1   0.045       0
   304.1    0.06       0     320     0.1       0
Bank Sta=291.1,304.1
XS Rating Curve= 0 ,0
Exp/Cntr(USF)=0,0
Exp/Cntr=0.3,0.1

Type RM Length L Ch R = 1 ,2000    ,498.2,498.2,498.2
XS GIS Cut Line= 6
1658961.60057984352488.6900059281659136.43914093352301.351797923
 1659204.6696475352228.2449887541659254.28240918352170.397991583
1659298.32923709 352088.499533341659339.10802692351997.806473255
#Sta/Elev= 30
       0 1097.39    21.7 1085.05    91.6  1037.5   120.8 1021.46   150.2 1000.31
   173.7  989.49   179.6  986.05   213.6   959.4   232.3  943.14   262.8  920.65
   268.3  918.27   287.7     918   298.3915.1109   302.7  914.71   308.5  915.11
     323  918.67   408.6  917.57   416.8  918.83   426.6  924.09   444.8  937.79
   457.3  945.66   470.9  958.93   498.2  974.24   520.8  990.59   538.9  998.18
   551.7  1004.6   569.6 1017.39   582.4 1024.34   595.6  1029.2   624.9 1036.75
#Mann= 5, -1 ,  0
       0     0.1       0  191.25    0.06       0  296.25     0.1       0
   298.3   0.045       0   308.5     0.1       0
Bank Sta=298.3,308.5
XS Rating Curve= 0 ,0
Exp/Cntr(USF)=0,0
Exp/Cntr=0.3,0.1

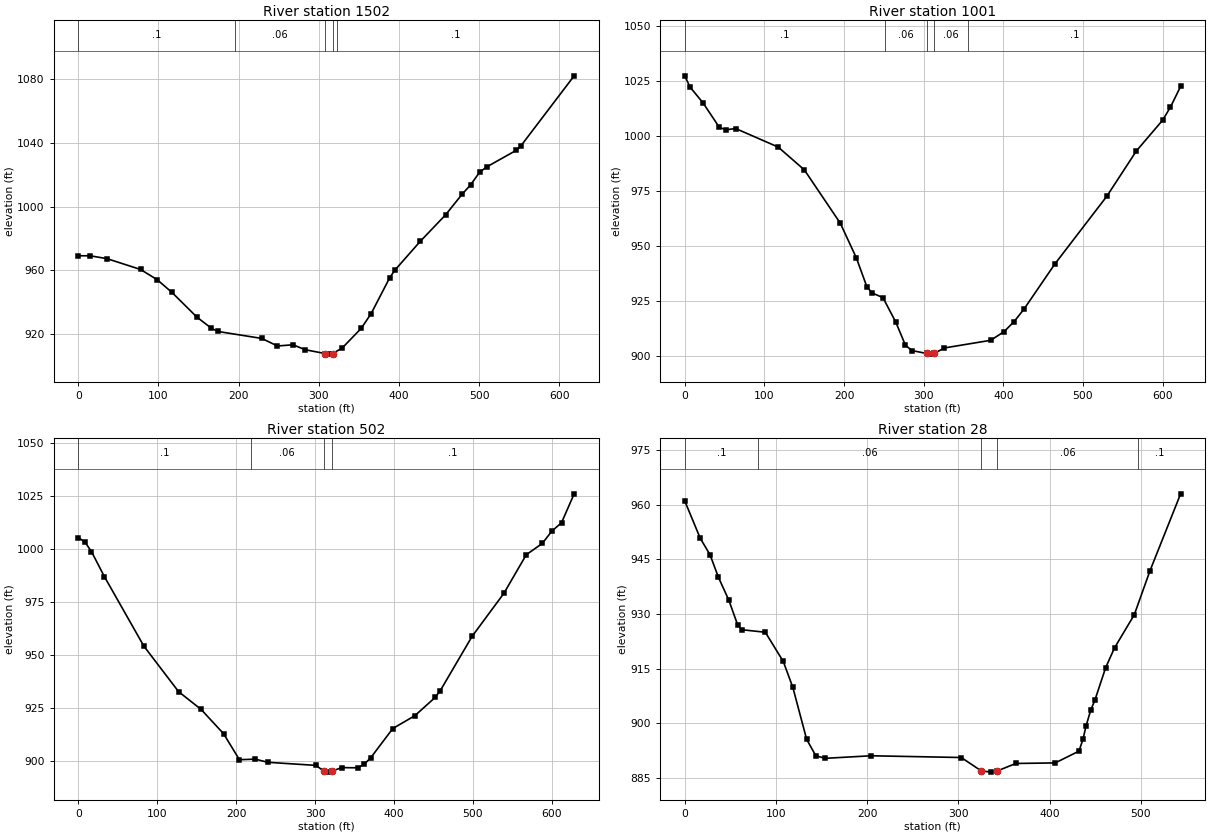
Type RM Length L Ch R = 1 ,1502    ,500.8,500.8,500.8
XS GIS Cut Line= 6
 1659332.6812025352689.7420972591659406.22600292352627.993861169
  1659475.592334352570.9923347531659535.99838117352524.057389259
1659613.88142751352461.0732632581659812.19238259352298.884939343
#Sta/Elev= 30
       0   969.2    14.9  969.16    35.8  967.37    77.6   960.6    98.5  954.15
   116.9  946.17   148.1  930.64   165.8  923.81   173.7  921.74   228.9  917.33
   248.5  912.59   267.9  913.36     283  910.26   308.2  907.83   313.9  907.49
   317.2907.8163   329.3  911.35   353.1  923.72   365.4  932.95   388.6  955.46
   394.9  960.12   426.5  978.15   458.2  994.83     479 1007.87   489.4  1013.6
   500.9 1021.72     510 1025.04   546.4 1035.32   552.1 1038.03   618.7 1082.06
#Mann= 5, -1 ,  0
       0     0.1       0  195.81    0.06       0   308.2   0.045       0
   317.2    0.06       0  322.31     0.1       0
Bank Sta=308.2,317.2
XS Rating Curve= 0 ,0
Exp/Cntr(USF)=0,0
Exp/Cntr=0.3,0.1

Type RM Length L Ch R = 1 ,1001    ,499.1,499.1,499.1
XS GIS Cut Line= 6
1659876.74113801353110.8790502551659933.49332109352861.081649587
1659953.69997358352762.9939192531659977.00242043352689.867753178
 1660011.9656051352605.8318320071660054.66269818   352517.056419
#Sta/Elev= 30
       0  1027.5     6.5 1022.42    22.9  1015.2    43.4 1004.06    51.6 1002.98
    63.9 1003.54   117.3  995.11   150.1  984.75   195.2  960.54   215.4  944.77
   228.7  931.54   235.4  928.78   248.8  926.68   264.9  915.58   277.1  905.01
   285.3  902.61   303.7 901.294   309.8     901     313  901.29   326.1  903.82
   384.1  907.28   400.9  911.22   413.5  915.79   426.1  921.55   464.8  942.03
     530   972.8   567.1  993.39   600.1 1007.37   609.8 1013.27   622.6 1022.69
#Mann= 5, -1 ,  0
       0     0.1       0  251.19    0.06       0   303.7   0.045       0
     313    0.06       0  356.16     0.1       0
Bank Sta=303.7,313
XS Rating Curve= 0 ,0
Exp/Cntr(USF)=0,0
Exp/Cntr=0.3,0.1

Type RM Length L Ch R = 1 ,502     ,474.3,474.3,474.3
XS GIS Cut Line= 6
1660374.07216434353272.6730180081660412.46152325353088.342349917
1660417.34176284353010.4579912571660396.53832676352912.549394429
1660389.72009893352837.104007259  1660415.712501352652.760872006
#Sta/Elev= 30
       0 1005.53     8.4 1003.36    16.6  998.94      33  987.11      83  954.34
   127.1  932.81   155.6  924.44   184.1  912.98   204.2  900.71   224.2  900.97
   240.2  899.49   301.1  898.03   311.4895.3049   317.4  894.85   321.5  895.31
   333.8  896.99   354.2  896.88   362.4   898.6   370.6  901.61   398.6  915.42
   426.7  921.51   452.2  930.06   458.9  933.36   499.1  958.89   539.4   979.2
   567.8   997.4   588.1 1002.76   600.3 1008.57   612.5 1012.54   628.5 1026.15
#Mann= 4, -1 ,  0
       0     0.1       0  218.34    0.06       0   311.4   0.045       0
   321.5     0.1       0
Bank Sta=311.4,321.5
XS Rating Curve= 0 ,0
Exp/Cntr(USF)=0,0
Exp/Cntr=0.3,0.1

Type RM Length L Ch R = 1 ,28      ,,,
XS GIS Cut Line= 5
1660618.37204641353326.5214876261660716.82250181353198.204040134
1660786.51215002353130.7267617121660903.76774859353056.612373936
1660847.35231909352921.657817091
#Sta/Elev= 30
       0  961.01    16.9  950.81    27.7  946.24    36.9  940.06    48.3  933.79
      58  926.97    62.6  925.68    88.3  924.99     108  916.96   118.5  909.83
   133.6  895.59   143.7  891.08     154  890.38   204.4  891.08   303.2   890.6
   325.1886.9258   336.3  886.59   342.7  886.92     363  888.97   406.2  889.12
   432.2  892.35   436.6  895.58     440  899.26   445.2  903.67   449.6  906.29
   461.5  915.27   471.2   920.7   492.9   929.8     510  941.81   543.7  962.99
#Mann= 5, -1 ,  0
       0     0.1       0      80    0.06       0   325.1   0.045       0
   342.7    0.06       0  497.45     0.1       0
Bank Sta=325.1,342.7
XS Rating Curve= 0 ,0
Exp/Cntr(USF)=0,0
Exp/Cntr=0.3,0.1
LCMann Table=0

Chan Stop Cuts=-1
Use User Specified Reach Order=0
Composite Channel Slope=5